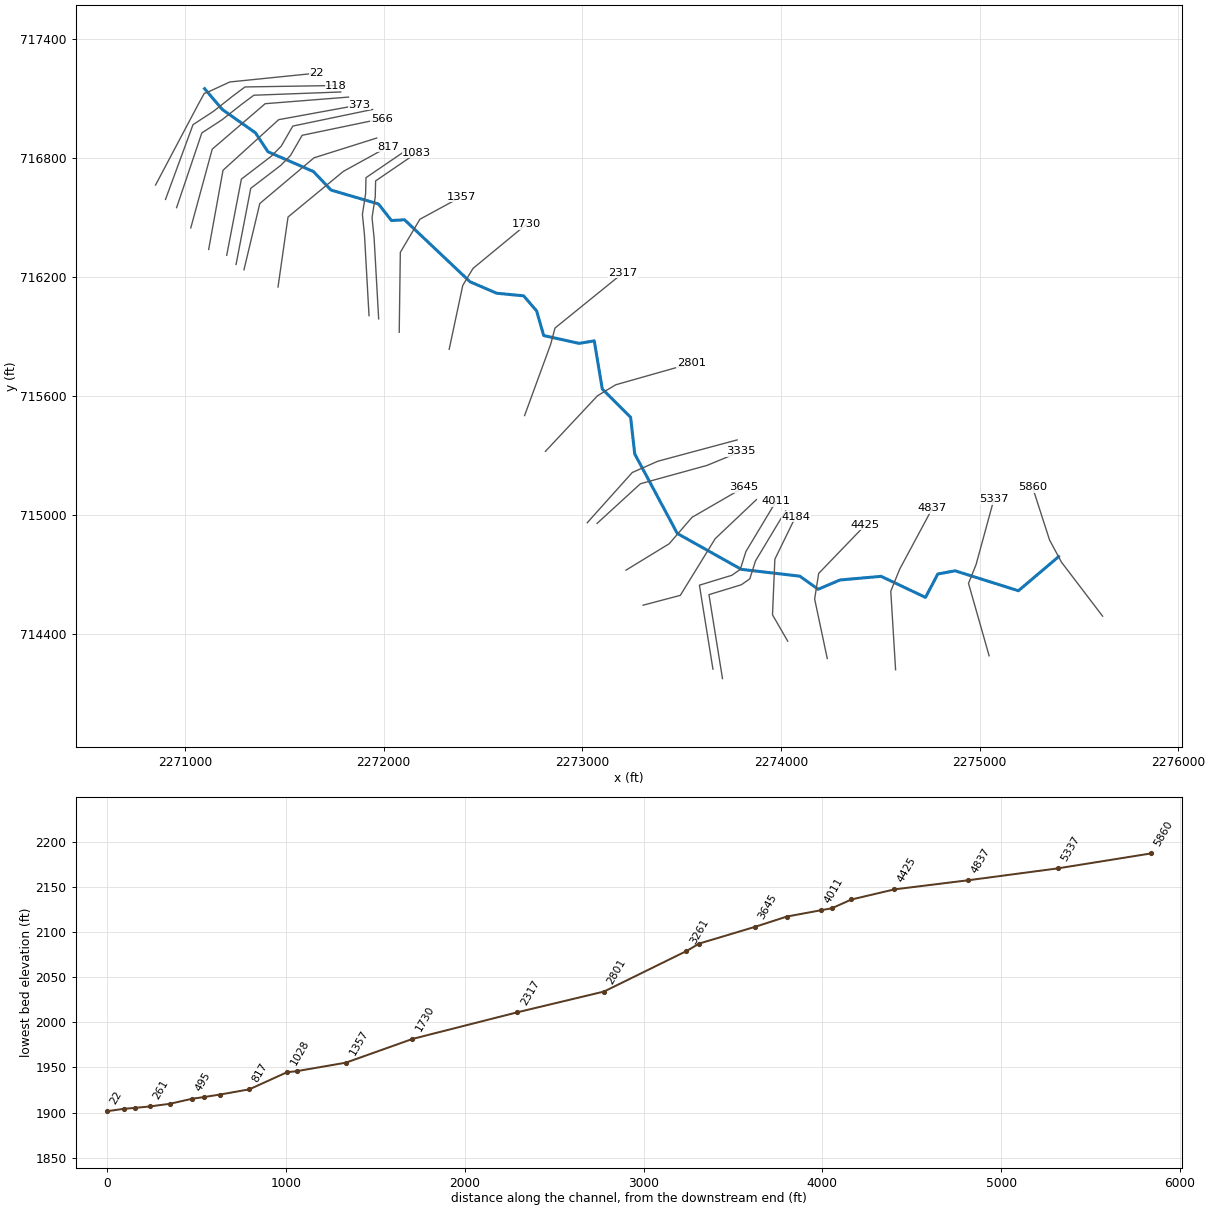
--- BEAVCK2T1.prj (project) ---

Proj Title=BEAVCK2T1
Current Plan=p01
Default Exp/Contr=0,0
English Units
Geom File=g01
Flow File=f01
Plan File=p01
BEGIN DESCRIPTION:
----------MODEL BY WOOD PLC 2022----------
AFH study
Randolph County, WV
HEC-RAS Version: RAS 6.2
Vertical Datum: NAVD88
Projection: NAD 1983 StatePlane West Virginia S FIPS 4702 (US Feet)
Terrain: 1-meter LIDAR (FEMA Region III 3DEP collected 2016-2018)
Land Use: 2019 NLCD
Hydrologic Method:
WV SIR2010-5033 regression equations
Additional Model Notes:
None
END DESCRIPTION:
DSS Export Rating Curves= 0
DSS Export Rating Curve Sorted= 0
DSS Export Volume Flow Curves= 0
DXF OffsetX= 0
DXF OffsetY= 0
DXF ScaleX= 0
DXF ScaleY= 0

--- BEAVCK2T1.p01 (plan) ---

Plan Title=Floodplain
Program Version=6.20
Short Identifier=Floodplain
Geom File=g01
Flow File=f01
Subcritical Flow
K Sum by GR= 0
Std Step Tol= 0.01
Critical Tol= 0.01
Num of Std Step Trials= 20
Max Error Tol= 0.3
Flow Tol Ratio= 0.001
Split Flow NTrial= 30
Split Flow Tol= 0.02
Split Flow Ratio= 0.02
Log Output Level= 0
Friction Slope Method= 1
Unsteady Friction Slope Method= 2
Unsteady Bridges Friction Slope Method= 1
Parabolic Critical Depth
Global Vel Dist= 0 , 0 , 0
Global Log Level= 0
CheckData=True
Encroach Param=-1 ,0,0, 0
Mapping Interval=1HOUR
Computation Time Step Use Courant=        0
Computation Time Step Use Time Series=    0
Computation Time Step Count To Double=0
Computation Time Step Max Doubling=0
Computation Time Step Max Halving=0
Computation Time Step Residence Courant=0
Run HTab= 0
Run UNet= 0
Run Sediment= 0
Run PostProcess= 0
Run WQNet= 0
Run RASMapper=-1
UNET Theta= 0
UNET Theta Warmup= 0
UNET ZTol= 0
UNET ZSATol= 0
UNET MxIter= 0
UNET Max Iter WO Improvement= 0
UNET MaxInSteps= 0
UNET DtIC= 0
UNET DtMin= 0
UNET MaxCRTS= 0
UNET WFStab= 0
UNET SFStab= 0
UNET WFX= 1
UNET SFX= 1
UNET Gravity=32.174
UNET 1D Methodology=Finite Difference
UNET DSS MLevel= 1
UNET Pardiso=0
UNET DZMax Abort= 0
UNET Use Existing IB Tables= 0
UNET Froude Reduction=False
UNET Froude Limit= 0
UNET Froude Power= 0
UNET D1 Cores= 0
UNET WindReference=Eulerian
UNET WindDragFormulation=Hsu (1988)
UNET D2 Coriolis=0
UNET D2 Cores= 0
UNET D2 Theta= 1
UNET D2 Theta Warmup= 1
UNET D2 Z Tol= 0.01
UNET D2 Volume Tol= 0.01
UNET D2 Max Iterations= 20
UNET D2 Equation= 0
UNET D2 RampUpFraction=0.1
UNET D2 TimeSlices= 1
UNET D2 Turbulence Formulation=Non-Conservative (original)
UNET D2 Eddy Viscosity=0.3
UNET D2 Transverse Eddy Viscosity=0.1
UNET D2 Smagorinsky Mixing=0
UNET D2 BCVolumeCheck=0
UNET D2 Cores=0
UNET D2 SolverType=PARDISO (Direct)
UNET D2 Minimum Iterations= 2147483647
UNET D2 Maximum Iterations= 2147483647
UNET D2 Restart Number= 10
UNET D2 Relaxation Coeff=1.3
UNET D2 SOR Precondition Iterations= 10
UNET D2 ILUT Maximum Fill= 8
UNET D2 ILUT Tolerance=1E-08
UNET D1D2 MaxIter= 0
UNET D1D2 ZTol=0.01
UNET D1D2 QTol=0.1
UNET D1D2 MinQTol=1
Write IC File= 0
Write IC File at Fixed DateTime=0
Write IC File at Sim End=0
Echo Input=False
Echo Parameters=False
Echo Output=False
Write Detailed= 0
HDF Write Warmup=0
HDF Write Time Slices=0
HDF Flush=0
HDF Compression= 1
HDF Chunk Size= 1
HDF Spatial Parts= 1
HDF Use Max Rows=0
HDF Fixed Rows= 1
Calibration Method= 0
Calibration Iterations= 20
Calibration Max Change=0.05
Calibration Tolerance=0.2
Calibration Maximum=1.5
Calibration Minimum=0.5
Calibration Optimization Method= 1
WQ AD Non Conservative
WQ ULTIMATE=-1
WQ Max Comp Step=1HOUR
WQ Output Interval=15MIN
WQ Output Selected Increments= 0
WQ Output face flow=0
WQ Output face velocity=0
WQ Output face area=0
WQ Output face dispersion=0
WQ Output cell volume=0
WQ Output cell surface area=0
WQ Output cell continuity=0
WQ Output cumulative cell continuity=0
WQ Output face conc=0
WQ Output face dconc_dx=0
WQ Output face courant=0
WQ Output face peclet=0
WQ Output face adv mass=0
WQ Output face disp mass=0
WQ Output cell mass=0
WQ Output cell source sink temp=0
WQ Output nsm pathways=0
WQ Output nsm derived pathways=0
WQ Create Restart=0
WQ Fixed Restart=0
WQ System Summary=0
WQ Write To DSS=0
Sorting and Armoring Iterations= 10
XS Update Threshold= 0.02
Bed Roughness Predictor= 0
Hydraulics Update Threshold= 0.02
Energy Slope Method= 1
Volume Change Method= 1
Sediment Retention Method= 0
Sediment TS Multiplier= 1
Warm Up Method= 0
XS Weighting Method= 0
Number of US Weighted Cross Sections= 1
Number of DS Weighted Cross Sections= 1
Upstream XS Weight=0
Main XS Weight=1
Downstream XS Weight=0
Number of DS XS's Weighted with US Boundary= 1
Upstream Boundary Weight= 1
Weight of XSs Associated with US Boundary= 0
Number of US XS's Weighted with DS Boundary= 1
Downstream Boundary Weight= 0.5
Weight of XSs Associated with DS Boundary= 0.5
Percentile Method= 0
Sediment Output Level= 3
Mass or Volume Output= 0
Output Increment Type= 1
Profile and TS Output Increment= 1
Transport Output Increment 1
XS Output Flag= 0
XS Output Increment= 10
Read HDF5 Sediment Hotstart= 0
Sediment Hotstart Type= 0
Write Gradation File= 0
Read Gradation Hotstart= 0
Write HDF5 File= 1
Write Binary Output= 1
Write DSS Sediment File= 0
DSS Sediment Output Type= 1
SV Curve= 0
Specific Gage Flag= 0
Subcell Erosion Methods= 0
Subcell Deposition Methods= 0
Advection Scheme= 1
Matrix Solver= 0
Implicit Weighting Factor= 1
Maximum Outer Loop Convergence Iterations= 5
Convergence Maximum Absolute= 0.001
Convergence RMSE= 0.0001
Grain Fractions Max Abs Error= 0.001
Max Subgrid Regions= 1
Max Subgrid Length Scale= 3.402823E+38
Initial Layer Thickness= 3.402823E+38
Min Layer Thickness= 3.402823E+38
Max Layer Thickness= 3.402823E+38
Number of Layers= 5

--- BEAVCK2T1.f01 (steady flow) ---

Flow Title=Flow
Program Version=6.20
Number of Profiles= 1
Profile Names=P100yr
River Rch & RM=BEAVCK2T1,Main,5860
     593
Boundary for River Rch & Prof#=BEAVCK2T1,Main            , 1
Up Type= 0
Dn Type= 3
Dn Slope=0.02844
DSS Import GetInterval= 0
DSS Import GetPeak= 0
DSS Import FillOption= 0

--- BEAVCK2T1.g01 (geometry) ---

Geom Title=Geometry
Program Version=6.20

River Reach=BEAVCK2T1       ,Main
Reach XY= 30
     2275397.433      714790.894     2275195.089      714619.279
     2274876.493      714719.766     2274789.424      714703.856
     2274727.415       714585.82     2274503.943      714691.935
     2274296.652      714673.446     2274187.079      714626.778
     2274094.829      714692.716     2273800.297      714727.092
 2273477.8056595714908.0016265392273263.72623727  715308.5617886
     2273242.846      715493.325     2273100.244      715635.733
2273060.04832109715878.056463516 2272983.6564521715865.415082358
     2272805.398      715904.845     2272769.842      716028.802
2272704.73080591716104.8964177272272568.68754899 716118.12422862
2272434.25073275 716175.94589952 2272104.8261205716488.087462542
2272039.03925362 716484.298402782271973.60219514716567.749178533
2271735.08532647716637.6248929452271646.27016039716731.094719698
2271417.09859452716830.988922211     2271354.701      716925.948
     2271187.375      717043.764     2271098.399      717148.505

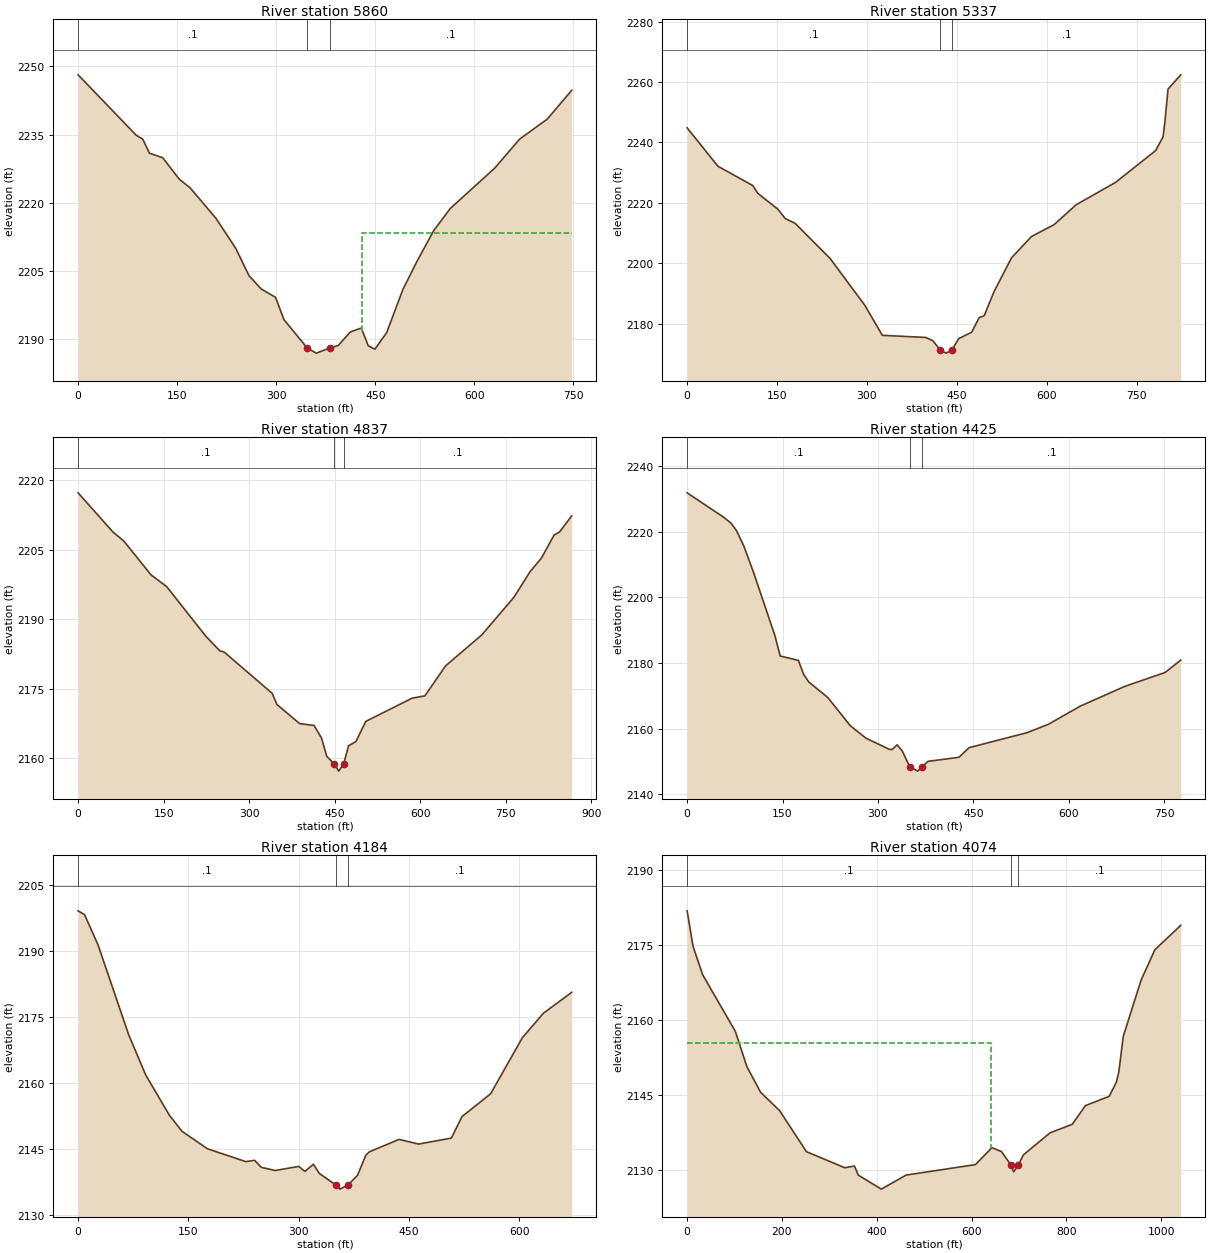
Type RM Length L Ch R = 1 ,5860    ,532.7,523.4,511.8
XS GIS Cut Line= 4
2275619.00047286714491.2345080812275411.66705716714763.656572186
2275351.91267441714875.0044344612275266.53023688 715140.27625787
#Sta/Elev= 30
       0 2248.14    87.9 2234.86      98 2233.96     108 2230.89   128.1  2229.9
   153.2 2225.17   169.8 2223.24   208.9 2216.53   238.7 2209.95   258.8 2203.92
   277.4 2200.99     299 2199.16   311.7 2194.25   347.3 2187.95   360.8 2186.88
   381.5 2188.04     394 2188.57   412.2 2191.54   428.8  2192.4   439.4 2188.49
   449.4 2187.75   467.2  2191.4     492 2200.95     513 2207.04   538.2 2213.78
   563.4  2218.7   630.7 2227.58   668.5 2233.98   710.5 2238.41   747.4 2244.73
#Mann= 3 ,-1,0
       0      .1       0   347.3    .045       0   381.5      .1       0
#XS Ineff= 2 , 0
                          430.32         2213.24
Permanent Ineff=
       F       F
Bank Sta=347.3,381.5
XS Rating Curve= 0 ,0
Exp/Cntr=0.3,0.1

Type RM Length L Ch R = 1 ,5337    ,498.9,499.5,499.9
XS GIS Cut Line= 4
2275047.70740171714291.7631644342274943.94615472714656.615198237
2274981.91752195714750.7856917142275072.29663899715081.626036423
#Sta/Elev= 30
       0 2244.85    51.4 2232.14   109.6 2225.74   117.9 2223.17   151.2 2217.97
   163.7 2214.83   180.3 2213.23   238.5 2201.64   296.7 2186.07   325.8 2176.16
   398.4 2175.46   410.1 2174.38  422.282171.321   432.2 2170.27  442.072171.323
   453.2 2175.07   474.8 2177.18   487.5 2182.03   495.8 2182.66   512.4 2190.71
   541.4 2201.81   574.6 2208.87   612.3 2212.78   649.2 2219.38     715 2226.79
   781.9 2237.32   794.3 2241.87   797.3  2246.7   802.6 2257.67   823.8  2262.4
#Mann= 3 ,-1,0
       0      .1       0  422.28    .045       0  442.07      .1       0
Bank Sta=422.28,442.07
XS Rating Curve= 0 ,0
Exp/Cntr=0.3,0.1

Type RM Length L Ch R = 1 ,4837    ,411,412.6,413.6
XS GIS Cut Line= 4
2274576.91198393 714221.278381362274552.63269738714617.183605345
2274597.67423157714728.4332179662274762.79393733715035.988149975
#Sta/Elev= 30
       0 2217.32      61 2208.87    80.1 2206.92   128.1 2199.56   155.4 2197.04
   224.3 2186.28   248.4 2183.19   256.4 2182.88   340.5 2173.97   348.6 2171.58
   388.6 2167.43   413.9 2167.03   426.9 2164.31   436.2 2160.33  449.46 2158.74
   457.1 2157.16  465.85 2158.74   474.3 2162.63   487.3 2163.56   504.5 2167.91
   585.6 2172.92   608.3 2173.44   644.6 2179.93   708.2 2186.63   764.3 2194.73
   792.6 2200.26   812.6 2203.21   834.8 2208.19   844.4 2208.86   865.7 2212.33
#Mann= 3 ,-1,0
       0      .1       0  449.46    .045       0  465.85      .1       0
Bank Sta=449.46,465.85
XS Rating Curve= 0 ,0
Exp/Cntr=0.3,0.1

Type RM Length L Ch R = 1 ,4425    ,238.9,240.4,239.8
XS GIS Cut Line= 4
2274232.85697708714278.0316903482274169.37619114714577.790114493
2274189.75654764714706.5863532972274424.92722988714950.918098139
#Sta/Elev= 30
       0 2231.82    56.4 2224.52    68.6 2222.67    77.5 2220.35    89.1 2215.64
   104.5 2207.53   138.2 2188.21   146.3 2182.12   174.9 2180.78   183.1 2176.55
   191.3 2174.19   221.1 2169.49   256.7 2160.85   281.2 2157.09   317.9  2153.7
     322 2153.62   330.1 2155.07   338.2  2153.2   349.9 2148.38   362.5 2147.06
  369.32 2148.39   378.7 2150.04   427.3 2151.27   443.2  2154.2   534.8  2158.8
   568.1 2161.35   618.1 2166.87   688.3 2172.89   751.3  2177.1   775.9 2180.87
#Mann= 3 ,-1,0
       0      .1       0   349.9    .045       0  369.32      .1       0
Bank Sta=349.9,369.32
XS Rating Curve= 0 ,0
Exp/Cntr=0.3,0.1

Type RM Length L Ch R = 1 ,4184    ,111.6,109.9,107.8
XS GIS Cut Line= 4
2274033.70923084714365.5877072612273957.24938023714498.046321708
2273969.09527258714778.0401408642274073.55450511 714992.34310245
#Sta/Elev= 30
       0 2199.05     8.8 2198.18    27.2 2191.29    68.8 2170.93    91.9 2161.82
   124.2 2152.64   141.4 2148.98   176.1 2145.02   228.1 2142.11   240.2  2142.4
   249.3 2140.81   268.2 2140.09   300.2 2141.02   308.6 2139.89   320.2 2141.51
   328.2 2139.42  350.47 2136.83   356.3 2135.86   367.42136.824   380.3 2139.02
   391.4 2143.54   396.3 2144.33   436.7 2147.15   463.4 2146.09   507.9 2147.45
   522.4 2152.34   561.3 2157.51   604.5 2170.24     633 2175.78   671.6 2180.55
#Mann= 3 ,-1,0
       0      .1       0  350.47    .045       0   367.4      .1       0
Bank Sta=350.47,367.4
XS Rating Curve= 0 ,0
Exp/Cntr(USF)=0,0
Exp/Cntr=0.3,0.1

Type RM Length L Ch R = 1 ,4074    ,67.5,63,63.1
XS GIS Cut Line= 6
2273705.49347062714176.7925228862273637.35639023 714599.67362492
2273800.58872373714649.550171266 2273842.9082176714679.274577675
2273871.62501701714769.4554038982274022.85577108715021.404214679
#Sta/Elev= 30
       0 2181.84    12.5 2174.73    32.8 2169.03   101.7  2157.7     126 2150.65
     155  2145.5   194.9 2141.85   251.6 2133.62   332.6  2130.4   352.9 2130.75
   360.8 2128.93   409.6 2126.12   461.7 2128.93     608 2131.03   642.8 2134.42
   662.8 2133.65   682.8 2130.96   688.5 2129.59   698.1  2130.9   709.2 2132.99
   765.4 2137.39   812.1  2139.1   840.1 2142.85   890.1  2144.7   905.4 2147.59
   910.5 2149.67   919.7  2156.7   957.2 2167.93   986.3 2174.04  1040.9 2178.93
#Mann= 3 ,-1,0
       0      .1       0   682.8    .045       0   698.1      .1       0
#XS Ineff= 2 , 0
          641.16 2155.41
Permanent Ineff=
       F       F
Bank Sta=682.8,698.1
XS Rating Curve= 0 ,0
Exp/Cntr(USF)=0,0
Exp/Cntr=0.3,0.1

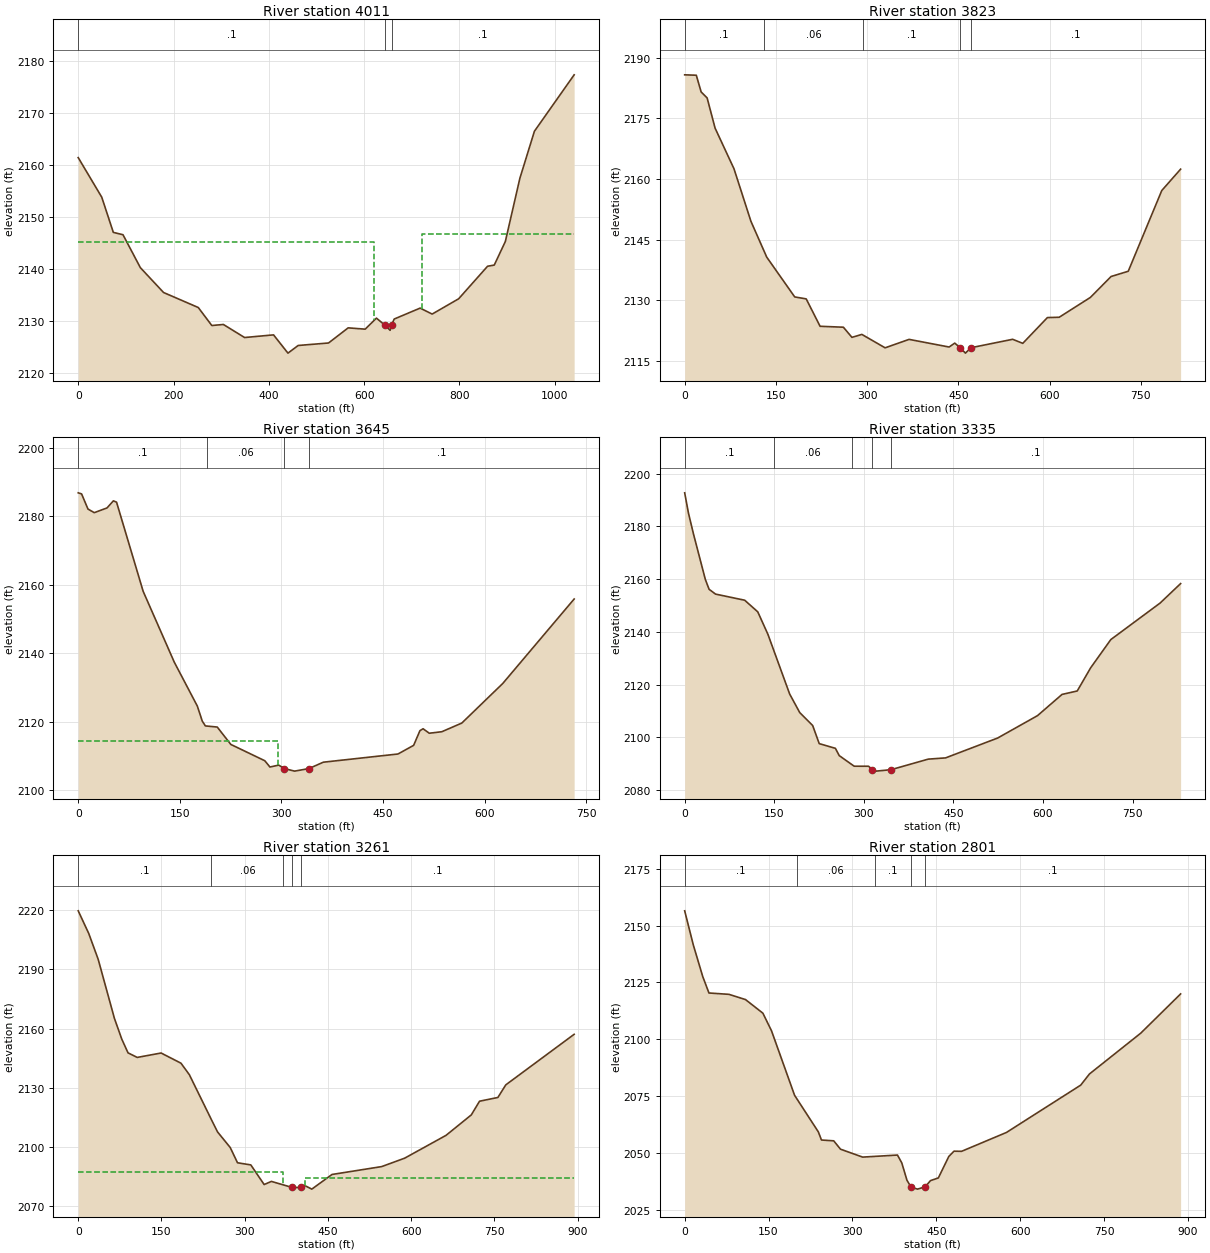
Type RM Length L Ch R = 1 ,4011    ,186.9,188.4,188.1
XS GIS Cut Line= 6
2273657.43061686 714224.401953492273589.29353648714647.283055523
2273752.52586998 714697.159601872273794.84536385714726.884008279
2273823.56216326714817.0648345022273974.79291733715069.013645282
#Sta/Elev= 30
       0 2161.49    49.4 2153.88    73.7 2147.11      94 2146.66   130.4 2140.33
   179.1 2135.55     252 2132.66   280.4  2129.2   304.7  2129.4   349.2 2126.89
     410  2127.4   440.2 2123.89   461.7 2125.36   525.4 2125.84   566.6 2128.75
   602.3  2128.5   625.9 2130.62  644.262129.231   654.6 2128.28   657.7 2129.29
   663.3 2130.45   717.7 2132.55   742.9  2131.4   798.5 2134.34   859.2  2140.6
   873.2 2140.82   896.5 2145.36     927 2157.52   957.5 2166.56  1040.9 2177.41
#Mann= 3 ,-1,0
       0      .1       0  644.26    .045       0   657.7      .1       0
#XS Ineff= 2 , 0
          621.23  2145.3  720.87          2146.8
Permanent Ineff=
       F       F
Bank Sta=644.26,657.7
XS Rating Curve= 0 ,0
Exp/Cntr(USF)=0,0
Exp/Cntr=0.3,0.1

Type RM Length L Ch R = 1 ,3823    ,180.6,178.4,173.9
XS GIS Cut Line= 4
2273305.72530104714546.5067904082273493.10578001714596.044158412
2273668.64036664714881.422474092 2273876.4819324715078.495046806
#Sta/Elev= 30
       0 2185.79    19.1 2185.69    27.1 2181.55    36.9 2180.08      50 2172.61
    81.1 2162.54   108.9 2149.57   134.9  2140.7   180.9 2130.86   199.8 2130.37
   222.6  2123.6   260.9 2123.37     275 2120.86   291.3 2121.59   329.5 2118.27
   368.9 2120.36   434.7 2118.47     444 2119.44     4532118.283   461.5 2116.96
  470.73  2118.3   539.2 2120.38   555.8 2119.38   596.3 2125.75   615.7 2125.83
     667 2130.74     701 2135.91   729.2 2137.21   784.3 2157.17   815.3 2162.46
#Mann= 5 ,-1,0
       0      .1       0     130     .06       0  293.82      .1       0
     453    .045       0  470.73      .1       0
Bank Sta=453,470.73
XS Rating Curve= 0 ,0
Exp/Cntr(USF)=0,0
Exp/Cntr=0.3,0.1

Type RM Length L Ch R = 1 ,3645    ,318.5,310.4,298.9
XS GIS Cut Line= 4
2273219.92217044714723.1186812242273437.29541675714856.158248679
 2273551.9652522714989.048855855 2273813.2432737715140.300278629
#Sta/Elev= 30
       0 2186.92       5  2186.6    14.4 2182.18    23.7 2181.12    42.5  2182.5
    51.9 2184.57    56.6  2184.2    95.9 2158.12   141.9 2137.39   175.9 2124.56
   183.2 2120.16   187.8 2118.76   205.3 2118.43   225.4 2113.34   275.5 2108.58
   283.1 2106.74     296  2107.3  304.432106.286   319.6 2105.54  340.662106.285
   361.9 2108.15   472.2 2110.55   495.3 2113.08   504.6 2117.37   509.2 2117.93
   518.4 2116.62   536.9 2117.06   566.4 2119.59   626.8 2131.15   732.3 2155.87
#Mann= 4 ,-1,0
       0      .1       0     190     .06       0  304.43    .045       0
  340.66      .1       0
#XS Ineff= 2 , 0
           295.6  2114.3
Permanent Ineff=
       F       F
Bank Sta=304.43,340.66
XS Rating Curve= 0 ,0
Exp/Cntr=0.3,0.1

Type RM Length L Ch R = 1 ,3335    ,72.4,73.7,75.6
XS GIS Cut Line= 4
2273074.01494106714958.4440147692273292.35027722715158.343365436
2273627.19055567715250.6126485942273800.19506454715321.926606302
#Sta/Elev= 30
       0  2192.7     6.3 2185.05    14.8 2177.04    34.6 2159.85    40.9 2156.11
    51.7 2154.29   100.5 2151.97   122.4 2147.56   139.4 2139.03   175.8  2116.4
   192.7 2109.35   214.4 2104.43   225.3 2097.58   252.4  2095.8   258.8 2093.04
   283.8 2089.02   307.9    2089   314.5  2087.7   320.7 2087.15   345.6  2087.7
   407.9  2091.7   436.9 2092.17     524 2099.69   590.9  2108.2   631.9 2116.24
   657.4 2117.55   679.8 2126.32   713.6 2137.04   796.2  2150.9   830.5 2158.28
#Mann= 5 ,-1,0
       0      .1       0     150     .06       0     280      .1       0
   314.5    .045       0   345.6      .1       0
Bank Sta=314.5,345.6
XS Rating Curve= 0 ,0
Exp/Cntr(USF)=0,0
Exp/Cntr=0.3,0.1

Type RM Length L Ch R = 1 ,3261    ,456.4,459.6,459.9
XS GIS Cut Line= 4
2273024.61122006714961.8893048492273251.25476312715214.904660837
2273379.76133367 715271.692712442273779.16357605715379.087618773
#Sta/Elev= 30
       0  2219.6      19 2208.12      36 2195.05    65.3  2165.1    78.5 2154.64
    89.8 2147.66   106.4 2145.36   149.4 2147.59   185.2 2142.44   200.3 2136.62
     240 2113.88   251.1 2107.64     274 2099.72   287.1 2092.01   311.1 2090.92
   335.1 2080.98   348.2 2082.57  385.692079.494  402.292079.493   408.8 2080.41
     421 2078.66   457.4 2086.08   546.9 2090.07   588.3 2094.33   662.9 2105.89
   708.4 2116.24   723.3 2123.19   756.3 2125.07   770.6 2131.46   893.8 2157.07
#Mann= 5 ,-1,0
       0      .1       0     240     .06       0  369.68      .1       0
  385.69    .045       0  402.29      .1       0
#XS Ineff= 2 , 0
          369.27 2087.46  409.49          2084.5
Permanent Ineff=
       F       F
Bank Sta=385.69,402.29
XS Rating Curve= 0 ,0
Exp/Cntr=0.3,0.1

Type RM Length L Ch R = 1 ,2801    ,473.1,483.9,490.5
XS GIS Cut Line= 4
2272814.07801018715321.5048194962273076.02554829715601.353081489
2273167.98932569715656.8764592012273549.03519068715764.952340654
#Sta/Elev= 30
       0 2156.49    15.4 2141.51    32.3 2127.56    43.4 2120.32    79.2 2119.72
   108.8 2117.42   139.9 2111.41   155.3 2103.66   196.5 2075.28     239 2059.18
   244.6 2055.59   266.5 2055.23   278.6 2051.56   318.2 2048.07   380.5 2048.97
   388.2 2045.52   397.5 2037.87  404.492034.956   416.2 2033.97  429.882034.957
   439.6 2037.72   453.6  2038.9   472.3 2048.35   481.6 2050.68   495.1 2050.61
   575.4 2058.92   708.2 2079.76   723.8 2084.67   815.6 2102.65   886.8 2119.91
#Mann= 5 ,-1,0
       0      .1       0     200     .06       0     340      .1       0
  404.49    .045       0  429.88      .1       0
Bank Sta=404.49,429.88
XS Rating Curve= 0 ,0
Exp/Cntr=0.3,0.1

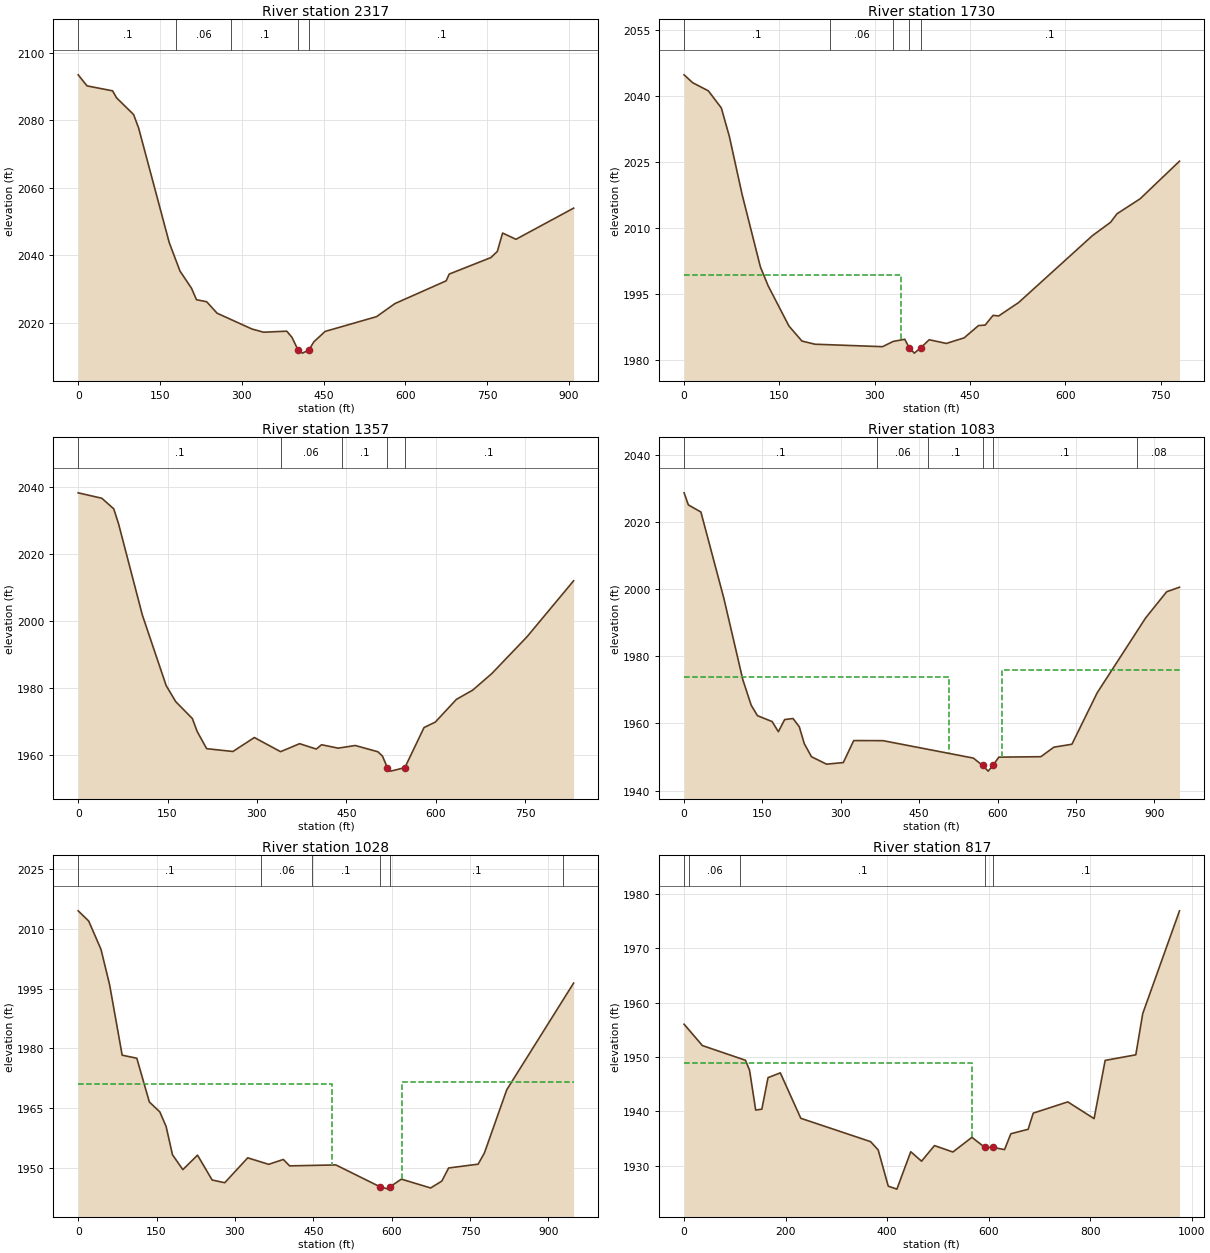
Type RM Length L Ch R = 1 ,2317    ,587.9,587.1,582
XS GIS Cut Line= 4
2272709.31110831715501.9381798492272840.54949991715861.109978413
2272862.32575921715942.7706449022273205.32208665716220.794632745
#Sta/Elev= 30
       0 2093.42    16.2 2090.15    63.1 2088.68    70.3 2086.62   101.6 2081.67
   110.8 2077.69   166.9 2043.78   186.6 2035.35   207.9 2030.21   216.9 2026.84
   235.6 2026.24   254.7 2022.85   318.6 2018.17   339.9 2017.22   382.4 2017.53
     392 2015.71  403.062011.969   411.2 2011.03  423.022011.969   432.1 2014.37
   452.8 2017.46     547 2021.82   580.8  2025.7   674.7 2032.43   680.4 2034.44
   756.6 2039.31   768.5 2041.12   778.2 2046.58   802.7 2044.73   908.4 2053.95
#Mann= 5 ,-1,0
       0      .1       0     180     .06       0     280      .1       0
  403.06    .045       0  423.02      .1       0
Bank Sta=403.06,423.02
XS Rating Curve= 0 ,0
Exp/Cntr=0.3,0.1

Type RM Length L Ch R = 1 ,1730    ,371.3,372.5,374.4
XS GIS Cut Line= 4
2272329.62037058715835.8320229592272398.04002661716157.536080584
2272449.56330748716242.9728282862272719.96128065716466.353387235
#Sta/Elev= 30
       0 2044.89    13.6 2043.09    38.2 2041.24    58.6 2037.34    71.2 2030.88
    91.3 2017.63     120 2001.17   132.2 1996.85     165 1987.67   185.4 1984.25
   205.9 1983.53   312.2 1982.97   328.9 1984.16   347.2 1984.66  354.071982.739
   362.2  1981.5  372.55 1982.74   385.6 1984.55   412.6 1983.71   440.6 1984.98
   463.2 1987.78   473.6 1987.88   486.1  1990.1   494.9 1989.97   526.3 1993.02
   642.3 2008.25   670.8 2011.28   681.1 2013.24   717.4 2016.65   779.4 2025.22
#Mann= 5 ,-1,0
       0      .1       0     230     .06       0   328.9      .1       0
  354.07    .045       0  372.55      .1       0
#XS Ineff= 2 , 0
          341.95 1999.36
Permanent Ineff=
       F       F
Bank Sta=354.07,372.55
XS Rating Curve= 0 ,0
Exp/Cntr=0.3,0.1

Type RM Length L Ch R = 1 ,1357    ,266.5,274.7,271.7
XS GIS Cut Line= 4
 2272078.1353644715921.5044064662272083.67764401716324.068711977
 2272182.2363591716490.7023197222272388.92568475716603.259399377
#Sta/Elev= 30
       0  2038.3    39.7 2036.68    59.7 2033.52    67.7  2029.1   107.7 2001.83
   147.7 1980.75   163.7 1975.97   191.7 1970.91   199.7 1967.06   215.7 1961.92
   259.7 1961.08   295.7 1965.25   339.7 1961.03   371.7 1963.41   399.7 1961.81
   408.5  1963.1   436.4 1962.08   465.1 1962.87   503.1    1961   510.8  1959.7
  518.911956.264   524.7 1955.22  548.341956.261   580.5 1968.22   599.5 1969.87
   634.8 1976.63   662.2  1979.4   694.1 1984.31   753.3 1995.31   831.6 2012.04
#Mann= 5 ,-1,0
       0      .1       0     340     .06       0   442.6      .1       0
  518.91    .045       0  548.34      .1       0
Bank Sta=518.91,548.34
XS Rating Curve= 0 ,0
Exp/Cntr=0.3,0.1

Type RM Length L Ch R = 1 ,1083    ,53.9,55,55.3
XS GIS Cut Line= 6
2271974.59502956715988.9826676842271951.75887936716395.514594252
2271941.25889677716498.6054391352271957.43036709716603.098016592
2271959.29630597716683.9553681962272166.24380006716825.245299085
#Sta/Elev= 30
       0  2028.6     8.2 2025.01    32.2 2022.89    76.3 1997.11   112.5 1972.98
   128.4 1965.44   140.4 1962.32   168.5 1960.56   180.5 1957.55   192.5 1961.16
   208.5 1961.47   220.5 1959.01   230.1 1953.98   243.8 1950.11   272.6 1947.89
   304.7 1948.36   324.7 1954.91   380.8 1954.88   553.6  1949.7  571.581947.498
     582 1945.82  591.171947.515   602.4 1949.98   682.8 1950.11   707.7 1952.94
   742.3 1953.82   790.7 1969.13   883.3 1991.37   923.6 1999.17   948.2 2000.53
#Mann= 6 ,-1,0
       0      .1       0     370     .06       0  467.17      .1       0
  571.58    .045       0  591.17      .1       0  867.58     .08       0
#XS Ineff= 2 , 0
          506.86 1973.88  609.39         1975.95
Permanent Ineff=
       F       F
Bank Sta=571.58,591.17
XS Rating Curve= 0 ,0
Exp/Cntr(USF)=0,0
Exp/Cntr=0.3,0.1

Type RM Length L Ch R = 1 ,1028    ,216.3,210.7,204.1
XS GIS Cut Line= 6
2271926.08061859716005.154138005 2271903.2444684716411.686064573
2271892.74448581716514.7769094562271908.91595613716619.269486913
2271910.78189501716700.1268385172272117.72938909716841.416769406
#Sta/Elev= 30
       0 2014.51    20.1 2011.95    43.6 2004.85    60.1 1995.97    84.2 1978.25
   112.2 1977.49   136.2  1966.5   156.3    1964   168.3 1960.33   180.5 1953.24
   200.3 1949.51   228.4 1953.14   256.4  1946.9   280.5 1946.22   324.5 1952.47
   364.6 1950.84   392.6 1952.06   404.7 1950.45   493.1 1950.69  577.141945.233
   594.1 1944.61   597.4 1945.25   618.6 1947.12   674.6  1944.9     696 1946.63
     709 1949.92   765.5 1950.88   777.5  1953.7   820.3 1969.58   948.2 1996.36
#Mann= 6 ,-1,0
       0      .1       0     350     .06       0  447.17      .1       0
  577.14    .045       0   597.4      .1       0  927.58     .08       0
#XS Ineff= 2 , 0
          486.64 1971.01  619.49         1971.48
Permanent Ineff=
       F       F
Bank Sta=577.14,597.4
XS Rating Curve= 0 ,0
Exp/Cntr(USF)=0,0
Exp/Cntr=0.3,0.1

Type RM Length L Ch R = 1 ,817     ,161.9,161.7,161.9
XS GIS Cut Line= 4
2271468.02624464716149.4747715292271518.38281217716502.048310817
 2271797.0250161716731.9218413692272023.57621689716856.854021758
#Sta/Elev= 30
       0 1956.01    36.1 1952.08   120.9 1949.38     129 1947.54   141.1 1940.22
   153.2 1940.38   165.4 1946.18   189.6 1947.06     230  1938.7   367.4 1934.41
   382.4 1932.89   402.3 1926.21   419.3 1925.67   446.6 1932.55   467.9 1930.81
   493.3 1933.68   529.6  1932.5   567.1  1935.2   592.6 1933.34  608.551933.345
   631.4 1932.94   643.8 1935.86   677.9 1936.68   687.9 1939.65     756 1941.72
   807.8 1938.64   829.6 1949.35     890 1950.38   903.7 1957.98   976.1 1976.87
#Mann= 5 ,-1,0
       0      .1       0      10     .06       0     110      .1       0
   592.6    .045       0  608.55      .1       0
#XS Ineff= 2 , 0
          567.51 1948.85
Permanent Ineff=
       F       F
Bank Sta=592.6,608.55
XS Rating Curve= 0 ,0
Exp/Cntr=0.3,0.1

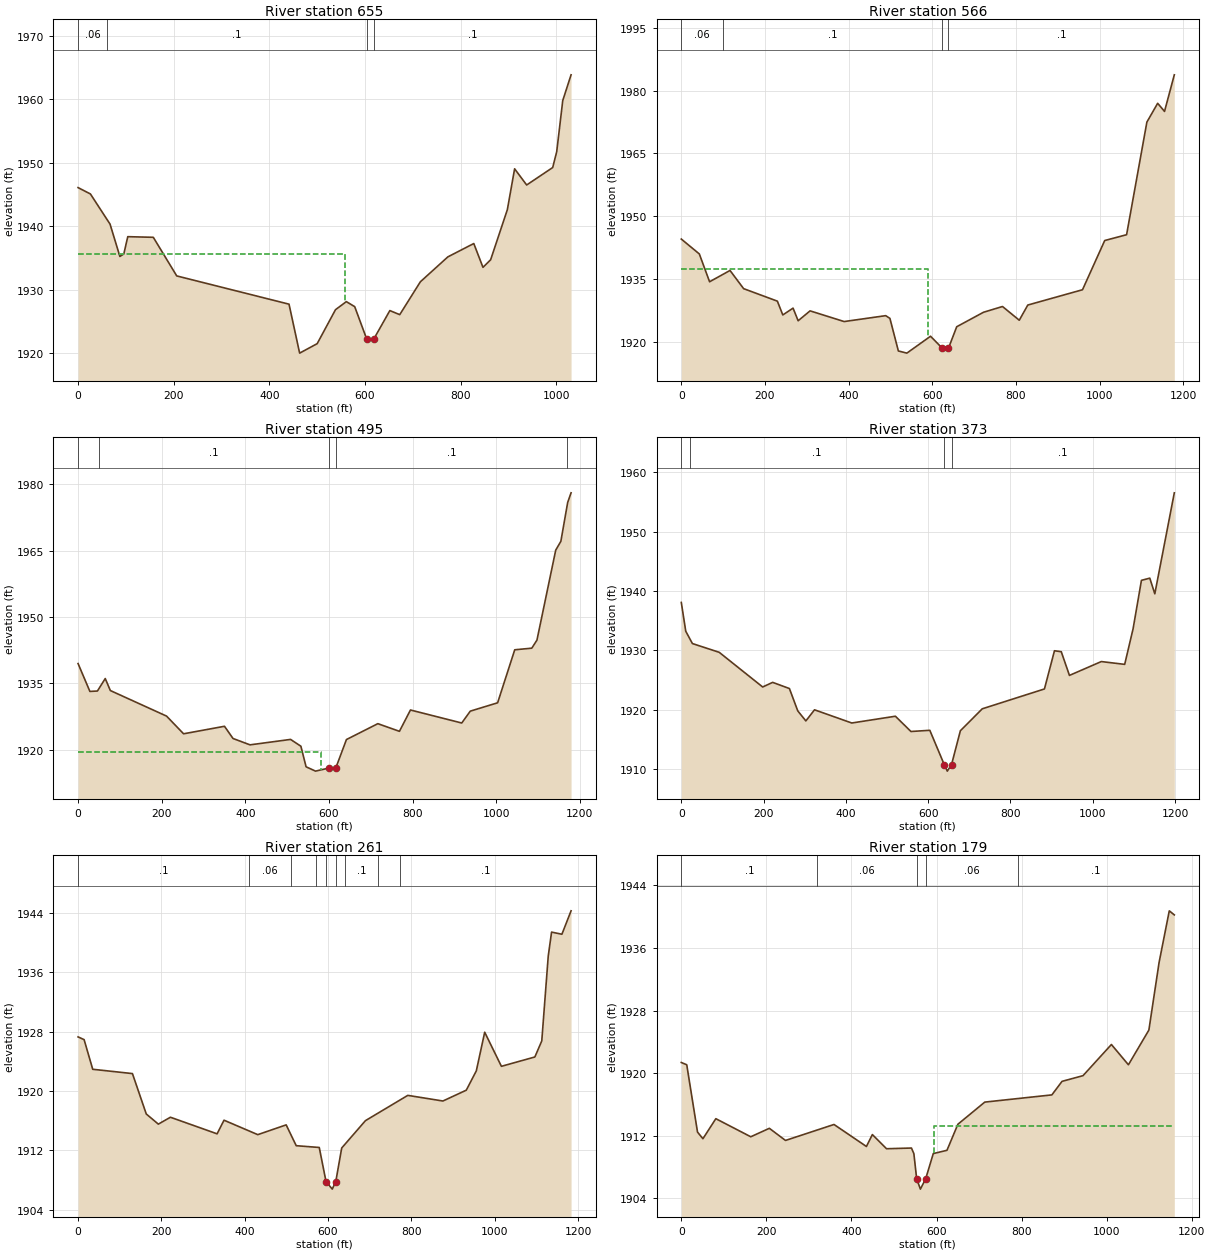
Type RM Length L Ch R = 1 ,655     ,88.1,89.3,87.8
XS GIS Cut Line= 4
2271296.51901496716236.0720188562271376.34259028716570.055008781
2271649.25062659716800.2630186862271964.83015015  716899.8505582
#Sta/Elev= 30
       0 1946.06    25.8 1945.06    66.9 1940.31    87.5 1935.21    95.7 1935.61
     104 1938.33   157.4 1938.23   206.4 1932.15   441.3  1927.7   463.5 1919.99
   500.2 1921.48   538.5 1926.83   561.2  1928.1   578.7 1927.31  603.941922.178
  618.32 1922.17   652.2 1926.69   672.9 1926.05   716.1 1931.23   773.6 1935.15
   827.8 1937.25     847  1933.5     863 1934.69     898 1942.58   913.2 1949.02
   938.4 1946.47   992.9 1949.22  1001.3 1951.73  1013.9 1959.77  1031.3 1963.82
#Mann= 4 ,-1,0
       0     .06       0      60      .1       0  603.94    .045       0
  618.32      .1       0
#XS Ineff= 2 , 0
          557.98 1935.65
Permanent Ineff=
       F       F
Bank Sta=603.94,618.32
XS Rating Curve= 0 ,0
Exp/Cntr(USF)=0,0
Exp/Cntr=0.3,0.1

Type RM Length L Ch R = 1 ,566     ,72,71.3,71.3
XS GIS Cut Line= 6
2271256.74485916716262.8240269582271330.60035359716646.343780526
2271481.87194206716762.2930691512271531.01601141716812.205014586
2271589.37459376716913.5646576222271991.08111224716997.285904931
#Sta/Elev= 30
       0  1944.5    43.1 1940.94    67.6 1934.29   116.5 1936.99     149 1932.64
   229.7 1929.65   242.7 1926.35   267.2 1927.98   279.4 1924.96   307.9 1927.33
   389.4 1924.77   488.7 1926.18   498.8 1925.53     519 1917.74   539.3 1917.22
   595.9 1921.26   624.4 1918.36   638.6 1918.33   658.5 1923.53   722.5 1926.99
     768 1928.37   808.1 1925.09   828.5 1928.72   959.3 1932.38  1012.4 1944.15
  1064.7 1945.54  1113.2 1972.47    1139 1976.97  1155.4 1975.03  1178.8 1983.78
#Mann= 4 ,-1,0
       0     .06       0     100      .1       0   624.4    .045       0
   638.6      .1       0
#XS Ineff= 2 , 0
           590.9 1937.46
Permanent Ineff=
       F       F
Bank Sta=624.4,638.6
XS Rating Curve= 0 ,0
Exp/Cntr(USF)=0,0
Exp/Cntr=0.3,0.1

Type RM Length L Ch R = 1 ,495     ,120.8,122.2,121.4
XS GIS Cut Line= 6
2271209.71060767716309.384475098 2271283.5661021716692.904228666
2271434.83769057716808.8535172912271483.98175992716858.765462726
2271542.34034228716960.1251057622271944.04686075717043.846353071
#Sta/Elev= 30
       0 1939.48    28.3 1933.18    46.3 1933.27      65 1936.09    77.2 1933.38
   211.6  1927.6   252.3  1923.6   350.1  1925.3   370.5 1922.54   411.2  1921.1
   508.1 1922.33   532.8 1920.79   545.2 1916.14   567.8 1915.16   600.2 1915.86
  616.231915.859   641.7  1922.3   716.8 1925.89   768.4 1924.16   794.8 1928.98
   917.4 1926.04   937.8 1928.72  1003.2 1930.61  1044.1 1942.59  1084.9 1942.96
  1097.2 1944.78  1142.1 1965.12  1154.4 1967.12  1170.7 1975.91  1178.8 1978.08
#Mann= 5 ,-1,0
       0     .06       0      50      .1       0   600.2    .045       0
  616.23      .1       0 1168.45     .08       0
#XS Ineff= 2 , 0
          580.95  1919.5
Permanent Ineff=
       F       F
Bank Sta=600.2,616.23
XS Rating Curve= 0 ,0
Exp/Cntr(USF)=0,0
Exp/Cntr=0.3,0.1

Type RM Length L Ch R = 1 ,373     ,112.8,112,111.3
XS GIS Cut Line= 4
2271118.81937993716338.5932757332271191.09078614716737.464933224
2271471.36555666716992.3997929832271878.77486641717066.886334891
#Sta/Elev= 30
       0 1938.07    10.8 1933.23      27 1931.15    92.1 1929.68   197.8 1923.84
   222.1 1924.62   262.8 1923.58   283.1 1919.82   302.8 1918.13   323.8    1920
   414.4 1917.78   520.4 1918.92   558.2 1916.35   604.1 1916.55  639.161910.776
   646.6 1909.68  656.851910.775   678.4 1916.48   731.6 1920.17   882.7 1923.51
   907.1 1929.94   923.6 1929.78   943.5 1925.79  1020.9 1928.12  1077.8 1927.65
  1098.2 1933.64  1118.5 1941.79  1138.8 1942.16    1151 1939.52  1198.4 1956.52
#Mann= 4 ,-1,0
       0     .06       0      20      .1       0  639.16    .045       0
  656.85      .1       0
Bank Sta=639.16,656.85
XS Rating Curve= 0 ,0
Exp/Cntr(USF)=0,0
Exp/Cntr=0.3,0.1

Type RM Length L Ch R = 1 ,261     ,80.2,81.2,79.7
XS GIS Cut Line= 4
2271028.84622516716447.2124550772271136.77983105716843.835946586
2271403.31312426717072.8349174242271822.86008815717106.161628929
#Sta/Elev= 30
       0 1927.29    14.5 1926.92    35.2 1922.92   130.5 1922.34   163.7 1916.89
   192.7 1915.52   221.7 1916.45   333.7 1914.21   350.3 1916.05   431.3  1914.1
   499.5 1915.42   523.6 1912.61   578.9 1912.37  595.131907.775   610.1 1906.75
  618.581907.775   632.8  1912.3   689.8 1915.99   791.4  1919.4   875.7 1918.64
   931.8  1920.1   955.9 1922.71     976 1927.92  1016.1 1923.32  1096.4 1924.58
    1113 1926.75  1128.5 1938.19  1136.5 1941.43  1161.3 1941.14  1183.3  1944.3
#Mann= 9 ,-1,0
       0      .1       0  411.05     .06       0  511.05      .1       0
  571.05     .06       0  595.13    .045       0  618.58     .06       0
  641.05      .1       0  721.05     .06       0  772.45      .1       0
Bank Sta=595.13,618.58
XS Rating Curve= 0 ,0
Exp/Cntr(USF)=0,0
Exp/Cntr=0.3,0.1

Type RM Length L Ch R = 1 ,179     ,62.1,61.6,64.1
XS GIS Cut Line= 6
 2270957.3282772716549.0712243342271084.43664993716925.467919229
2271187.42216386716992.7055155962271284.90814081 717069.78745086
2271346.37025259717115.5280552192271783.91366961717131.840015349
#Sta/Elev= 30
       0 1921.36    12.8 1921.07    38.1 1912.47    50.8 1911.62    81.2 1914.18
   163.3 1911.87     207 1912.95     245  1911.4     359 1913.44   435.2 1910.63
   449.2 1912.15   482.5 1910.34   541.1 1910.43   546.8 1909.71  553.361906.504
   562.1 1905.18  574.581906.505   592.4 1909.72   624.6 1910.14   650.3 1913.47
   713.5  1916.3   871.2 1917.22   895.1 1918.95   944.5 1919.68  1011.2 1923.66
  1051.2 1921.07  1099.3  1925.5  1123.3 1934.14  1147.3 1940.74  1159.1 1940.22
#Mann= 5 ,-1,0
       0      .1       0     320     .06       0  553.36    .045       0
  574.58     .06       0  791.21      .1       0
#XS Ineff= 2 , 0
                          595.23          1913.2
Permanent Ineff=
       F       F
Bank Sta=553.36,574.58
XS Rating Curve= 0 ,0
Exp/Cntr(USF)=0,0
Exp/Cntr=0.3,0.1

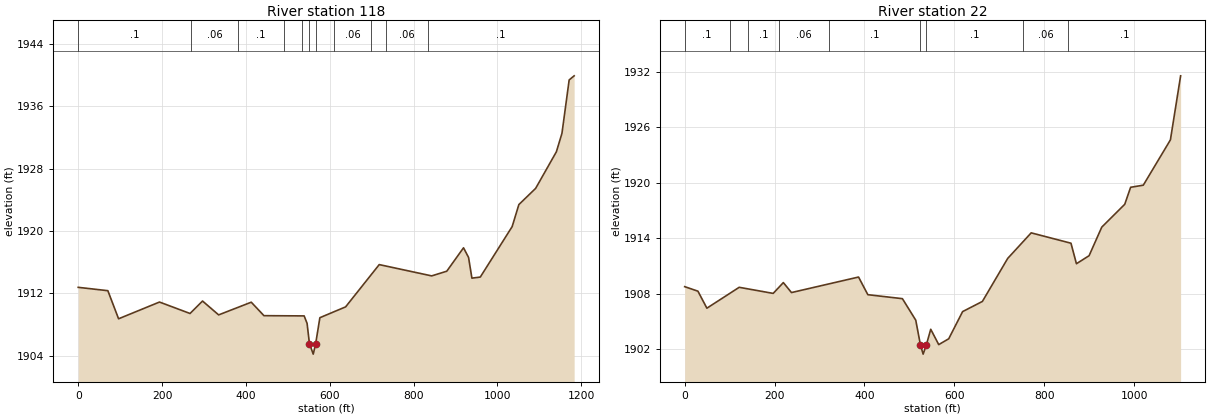
Type RM Length L Ch R = 1 ,118     ,99.1,95.9,95.6
XS GIS Cut Line= 6
2270901.65474168716590.7861540062271040.00118136716967.182848901
 2271142.9866953717034.4204452682271240.47267225717111.502380532
2271301.93478402717157.2429848922271760.07661451717164.426102692
#Sta/Elev= 30
       0 1912.77    70.7 1912.34    96.3 1908.73   193.9 1910.88   266.8 1909.41
   296.6 1911.01     335 1909.23   412.8 1910.86   443.1 1909.13     539  1909.1
     546 1908.14   551.61905.547   560.7 1904.19   566.51905.543   576.5 1908.87
   637.9 1910.26   718.1 1915.69   843.2 1914.24   879.2 1914.84   919.2 1917.85
   931.2 1916.61   939.2 1913.95   959.2 1914.09  1035.2 1920.57  1051.2  1923.4
  1091.2 1925.48  1140.7 1930.18    1154 1932.55  1171.2 1939.41  1183.1 1939.94
#Mann= 11 ,-1,0
       0      .1       0     270     .06       0     380      .1       0
  490.66     .06       0  534.05      .1       0   551.6    .045       0
   566.5      .1       0  610.94     .06       0  698.33      .1       0
  734.95     .06       0  834.95      .1       0
Bank Sta=551.6,566.5
XS Rating Curve= 0 ,0
Exp/Cntr(USF)=0,0
Exp/Cntr=0.3,0.1

Type RM Length L Ch R = 1 ,22      ,,,
XS GIS Cut Line= 6
2270851.47007687716663.1168898982271062.48003715717062.240642165
2271096.48678924717124.3623079352271119.84495931717133.532040322
2271225.39326234717182.3151364782271662.78907773717226.866477664
#Sta/Elev= 30
       0 1908.77    29.5 1908.28    49.4 1906.44   121.3  1908.7   196.9 1908.04
   219.5 1909.21   237.6 1908.13   386.8 1909.81   407.5  1907.9   484.4 1907.47
   514.1 1905.14   524.5 1902.46   530.5 1901.47  537.421902.433   547.4 1904.16
   565.2  1902.5   587.4 1903.13   618.3 1906.07   662.3 1907.17   718.7 1911.83
   770.9 1914.59   859.4 1913.47   871.5 1911.25   899.7 1912.12   927.9 1915.21
     979 1917.68   992.1 1919.52  1020.3 1919.75  1080.6 1924.65  1103.3 1931.58
#Mann= 9 ,-1,0
       0      .1       0     100     .06       0     140      .1       0
     210     .06       0     320      .1       0   524.5    .045       0
  537.42      .1       0  753.66     .06       0  853.66      .1       0
Bank Sta=524.5,537.42
XS Rating Curve= 0 ,0
Exp/Cntr(USF)=0,0
Exp/Cntr=0.3,0.1
LCMann Table=0

Chan Stop Cuts=-1
Use User Specified Reach Order=0
Composite Channel Slope=5